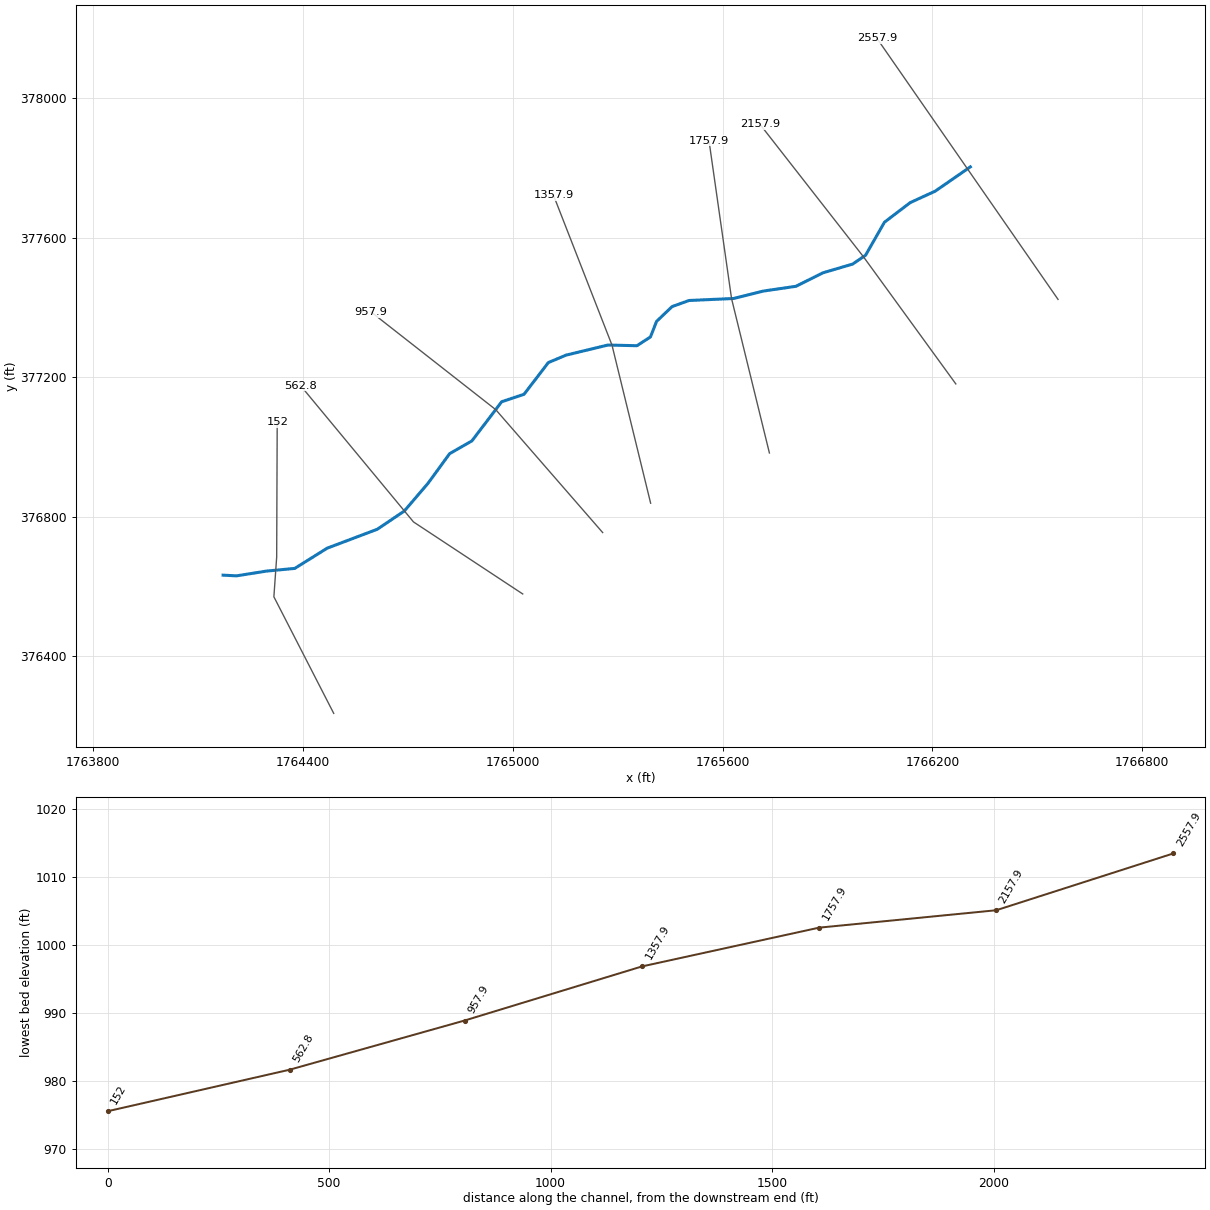
--- NP5.prj (project) ---

Proj Title=NP5
Current Plan=p01
Default Exp/Contr=0,0
English Units
Geom File=g01
Flow File=f01
Plan File=p01
BEGIN DESCRIPTION:
END DESCRIPTION:
DSS Export Rating Curves= 0
DSS Export Rating Curve Sorted= 0
DSS Export Volume Flow Curves= 0
DXF OffsetX= 0
DXF OffsetY= 0
DXF ScaleX= 0
DXF ScaleY= 0

--- NP5.p01 (plan) ---

Plan Title=Floodplain
Program Version=4.00
Geom File=g01
Flow File=f01
K Sum by GR=0
Std Step Tol=0.01
Critical Tol=0.01
Num of Std Step Trials=20
Max Error Tol=0.3
Flow Tol Ratio=0.001
Split Flow NTrial=30
Split Flow Tol=0.02
Split Flow Ratio=0.02
Log Output Level=0
Friction Slope Method=1
Unsteady Friction Slope Method=2
Unsteady Bridges Friction Slope Method=1
Global Log Level=0
CheckData=False
Run HTab=0
Run UNet=0
Run PostProcess=0
UNET Theta=0
UNET Theta Warmup=0
UNET ZTol=0
UNET ZSATol=0
UNET MxIter=0
UNET MaxInSteps=0
UNET DtIC=0
UNET DtMin=0
UNET MaxCRTS=0
UNET WFStab=0
UNET SFStab=0
UNET WFX=0
UNET SFX=0
UNET DSS MLevel=0
UNET DZMax Abort=0
UNET Convert EG Bridges=0
UNET Use Existing IB Tables=0
UNET Froude Limit=0
UNET Froude Power=0
Write IC File=0
Echo Input=False
Echo Output=False
Write Detailed=0

--- NP5.f01 (steady flow) ---

Flow Title=NFF Regression Equation
Program Version=4.00
Number of Profiles=1
Profile Names=P100yr
River Rch & RM=NP5,Main      ,2557.9
713.3875
River Rch & RM=NP5,Main      ,1757.9
759.9212
River Rch & RM=NP5,Main      ,152
839.8998
Boundary for River Rch & Prof#=NP5,Main      ,1
Up Type=0
Dn Type=3
Dn Slope=0.017511

--- NP5.g01 (geometry) ---

Geom Title=USGS 3m DEM
Program Version=4.00

River Reach=NP5             ,Main
Reach XY= 30
     1766308.441      377802.504     1766207.866      377732.875
     1766136.304      377699.995     1766062.807      377643.905
     1766008.651      377549.133     1765971.903      377523.989
     1765886.801      377498.846     1765809.436      377460.163
     1765716.598      377446.624     1765631.496      377425.349
     1765503.844      377419.546      1765455.49      377402.139
     1765411.005      377359.588     1765393.598      377315.103
     1765354.916       377289.96     1765271.748      377291.894
     1765151.832      377262.882     1765101.545      377241.607
     1765031.916      377150.702      1764968.09      377129.427
     1764882.988      377017.248     1764819.162      376980.499
      1764757.27      376895.397     1764689.575      376816.098
      1764612.21      376763.877     1764469.084      376709.721
     1764376.246      376651.697     1764295.013      376643.961
     1764209.911      376630.422     1764171.229      376632.356

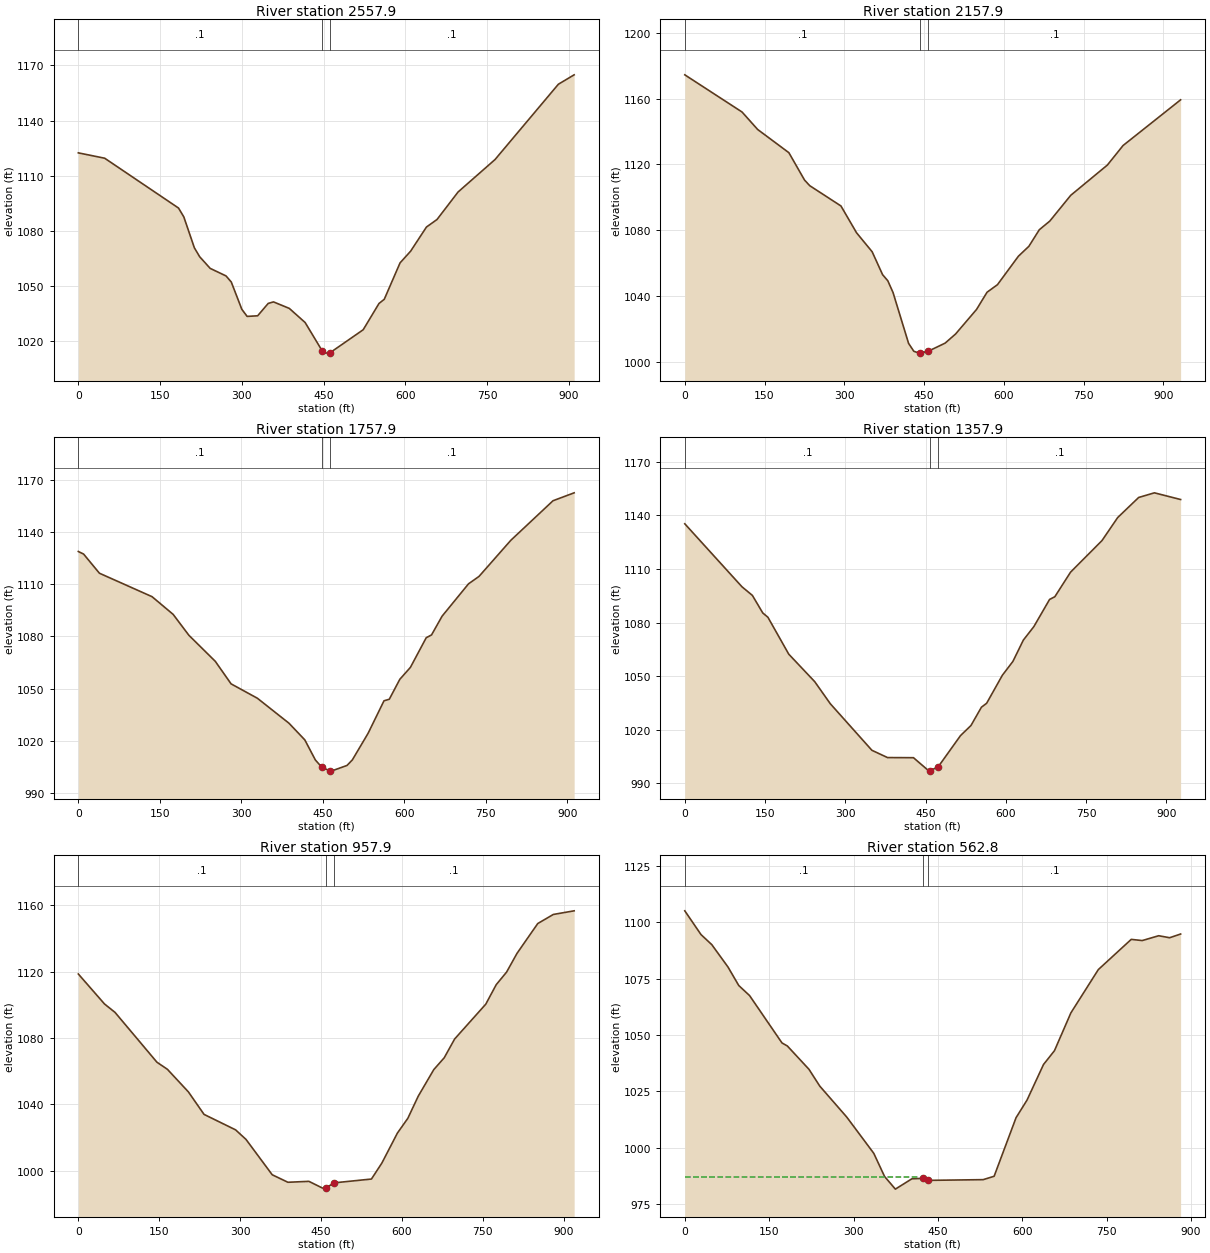
Type RM Length L Ch R = 1 ,2557.9  ,399.555,400,401.23
XS GIS Cut Line= 3
     1766559.209      377422.714     1766300.219      377796.812
     1766041.229      378170.909
#Sta/Elev= 30
       0 1122.42    48.4  1119.5   183.9 1092.39   193.6 1087.58     213 1070.74
   222.7  1065.9     242 1059.56   271.1 1055.45   280.7 1052.15   300.1 1037.28
   309.8 1033.43   329.1 1033.76   348.5  1040.5   358.2 1041.32   387.2 1037.79
   416.3 1030.09   447.5 1014.71     455 1013.45   462.5 1013.77   522.8 1026.17
   551.8 1040.45   561.5 1042.75   590.5 1062.57   609.9 1068.93   638.9 1082.05
   658.3 1086.16     697 1101.14   764.8 1118.79     881 1159.75     910 1164.88
#Mann= 3 , 0 , 0
       0      .1       0   447.5    .045       0   462.5      .1       0
Bank Sta=447.5,462.5
XS Rating Curve= 0 ,0
Exp/Cntr=0.3,0.1

Type RM Length L Ch R = 1 ,2157.9  ,408.788,400,388.171
XS GIS Cut Line= 3
     1766266.843      377180.527     1766002.617      377545.004
     1765706.205      377925.261
#Sta/Elev= 30
       0 1174.59   107.7 1151.93     137 1141.31   195.7 1127.17   225.1 1110.53
   234.9 1107.08   293.6 1094.73     323 1078.37   352.3 1066.83   371.9 1052.89
   381.7 1049.18   391.5 1042.06   420.8 1011.03   430.6 1006.25   440.4  1005.1
   442.7 1005.13   457.7 1006.25   489.5 1011.19   509.2 1016.76   548.6 1031.71
   568.3 1042.17   587.9 1046.79   627.3 1064.12     647 1070.16   666.6 1080.25
   686.3 1085.51   725.7 1101.21   794.6 1119.65   824.1 1131.54   932.3 1159.37
#Mann= 3 , 0 , 0
       0      .1       0   442.7    .045       0   457.7      .1       0
Bank Sta=442.7,457.7
XS Rating Curve= 0 ,0
Exp/Cntr=0.3,0.1

Type RM Length L Ch R = 1 ,1757.9  ,400.455,400,405.125
XS GIS Cut Line= 3
     1765733.764      376982.507     1765625.498      377425.006
     1765561.029      377877.282
#Sta/Elev= 30
       0 1128.84     9.7 1127.37    38.8 1116.36   135.7 1102.86   174.5 1092.68
   203.5 1080.65     252  1065.7   281.1 1052.73   329.5 1044.45   387.7 1030.07
   416.8 1020.49   436.2 1008.95   448.1 1004.75   463.1 1002.69   465.3 1002.54
   494.4  1005.8   504.2 1008.98   533.3 1024.34   562.5    1043   572.2 1043.87
   591.6 1055.35   611.1 1062.22   640.2 1079.26     650 1080.89   669.4 1091.66
     718 1110.25   737.4 1114.54   795.8 1135.27   873.5 1158.04   912.4 1162.59
#Mann= 3 , 0 , 0
       0      .1       0   448.1    .045       0   463.1      .1       0
Bank Sta=448.1,463.1
XS Rating Curve= 0 ,0
Exp/Cntr=0.3,0.1

Type RM Length L Ch R = 1 ,1357.9  ,389.295,400,411.735
XS GIS Cut Line= 3
     1765394.093      376838.621     1765283.576      377291.619
     1765116.488      377720.615
#Sta/Elev= 30
       0 1135.34   106.9 1100.06   126.3 1095.26   145.7 1085.43   155.4 1082.98
   194.3 1062.34   242.9 1046.92     272 1034.56   349.7 1008.51   378.9 1004.43
   427.4 1004.36   456.6  996.84   458.8  997.08   473.8  999.34   515.3 1016.73
   534.9  1022.4   554.4 1032.63   564.2 1034.87   593.6 1050.56   613.2 1058.26
   632.8 1070.24   652.4 1077.77   681.8 1092.99   691.6  1094.5     721 1108.27
   779.7 1125.93   809.1 1138.85   848.3 1150.09   877.7 1152.69   926.7 1148.94
#Mann= 3 , 0 , 0
       0      .1       0   458.8    .045       0   473.8      .1       0
Bank Sta=458.8,473.8
XS Rating Curve= 0 ,0
Exp/Cntr=0.3,0.1

Type RM Length L Ch R = 1 ,957.9   ,395.652,395.173,390.335
XS GIS Cut Line= 3
     1765256.892      376754.466     1764951.076      377106.743
     1764594.691      377386.547
#Sta/Elev= 30
       0 1118.55    48.6 1100.48      68 1095.44   145.8 1065.39   165.2 1061.12
   204.1 1047.52   233.2 1033.93   291.6 1024.64     311 1018.86   359.6  997.56
   388.7  993.03   427.6  993.59   456.8   988.9     459  989.48     474  992.67
   543.6  994.98   562.9 1004.57   591.8 1022.69   611.1 1031.56   630.4  1044.9
   659.3 1060.95   678.6 1068.06   697.9 1079.37   755.7 1100.38     775 1112.09
   794.3 1119.71   813.6 1130.99   852.1 1148.97     881 1154.45   919.6 1156.63
#Mann= 3 , 0 , 0
       0      .1       0     459    .045       0     474      .1       0
Bank Sta=459,474
XS Rating Curve= 0 ,0
Exp/Cntr=0.3,0.1

Type RM Length L Ch R = 1 ,562.8   ,428.164,410.808,393.457
XS GIS Cut Line= 3
     1765028.248      376578.491     1764715.886      376784.922
      1764392.73      377175.868
#Sta/Elev= 30
       0    1105    28.8 1094.48      48 1090.01    76.8  1080.1      96 1071.89
   115.2 1067.44   172.8 1046.46   182.4  1045.1   220.8 1034.77     240 1027.32
     288 1013.59     336  997.54   355.2  987.28   374.4  981.67   403.7  986.23
   423.2  986.45   432.9  985.55   530.5  985.87     550  987.37     589 1013.33
   608.5 1021.13   637.8 1036.89   657.3 1043.03   686.5 1059.78   735.3 1078.97
   793.8 1092.35   813.3 1091.82   842.6 1093.96   862.1 1093.08   881.6 1094.72
#Mann= 3 , 0 , 0
       0      .1       0   423.2    .045       0   432.9      .1       0
#XS Ineff= 2 , 0
          413.77  986.93
Permanent Ineff=
       F       F
Bank Sta=423.2,432.9
XS Rating Curve= 0 ,0
Exp/Cntr=0.3,0.1

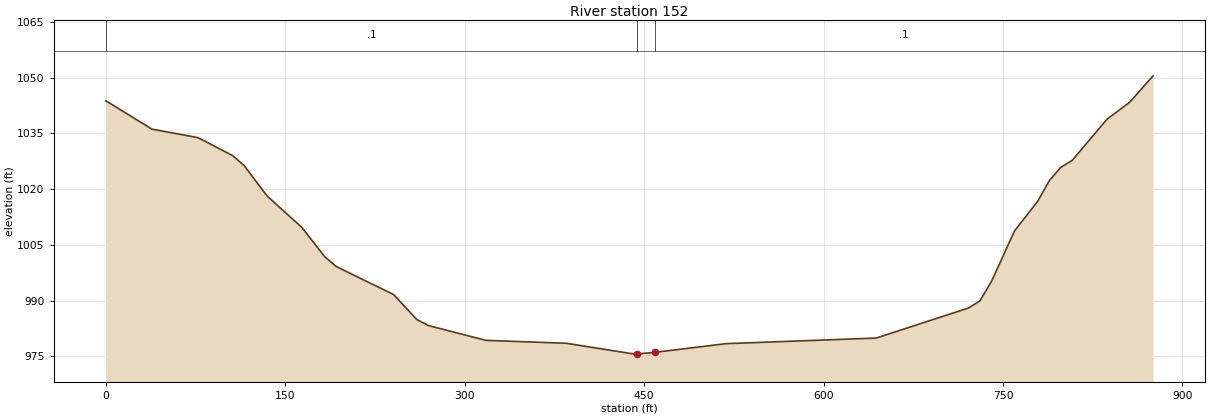
Type RM Length L Ch R = 1 ,152     ,151.496,151.967,152.437
XS GIS Cut Line= 4
     1764487.726      376236.252     1764316.607      376570.343
     1764324.601      376684.213     1764326.113      377070.121
#Sta/Elev= 30
       0 1043.76    38.5 1036.13      77 1033.84   105.9 1029.01   115.5 1026.35
   134.7 1018.16   163.6 1009.74   182.9 1001.81   192.5  999.16   240.6  991.59
   259.9  984.88   269.5  983.27   317.6  979.28   384.9  978.49     442  975.57
   444.2  975.62   459.2  976.06   518.5  978.39   643.9  979.89   721.1  987.98
   730.7   989.9   740.4   995.2   759.7 1008.78   778.9 1016.66   788.6 1022.23
   798.2 1025.82   807.9 1027.75   836.8 1038.77   856.1 1043.44   875.4 1050.48
#Mann= 3 , 0 , 0
       0      .1       0   444.2    .045       0   459.2      .1       0
Bank Sta=444.2,459.2
XS Rating Curve= 0 ,0
Exp/Cntr=0.3,0.1

Chan Stop Cuts=-1
Use User Specified Reach Order=0